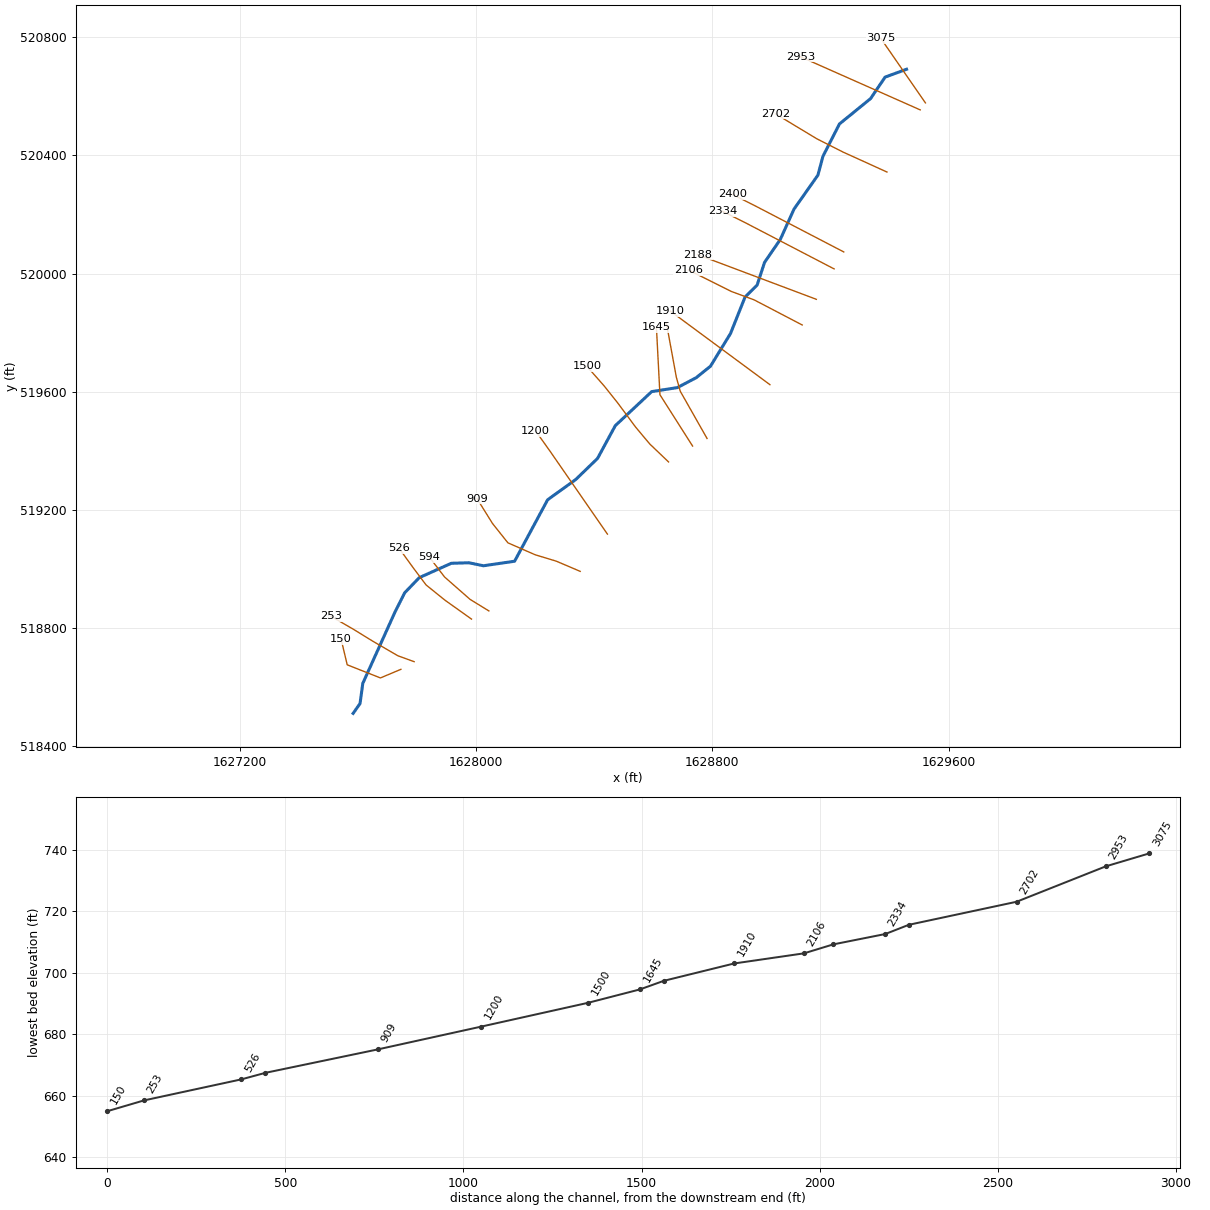
--- McLainRn.prj (project) ---

Proj Title=McLainRn
Current Plan=p01
Default Exp/Contr=0,0
English Units
Geom File=g01
Flow File=f01
Plan File=p01
BEGIN DESCRIPTION:
---------- MODELED AS PART OF WVEM CTP PROGRAM, 2025----------
Stream Name: McLain Run
Flood Zone: AFH
Marshall County, WV
HEC-RAS Version: RAS 6.6
Vertical Datum: NAVD88
Projection: NAD 1983 StatePlane West Virginia N FIPS 4701 (US Feet)
Terrain: 1-meter West Virginia FEMA R3 South Central (collected 2018-2019)
Land Use: 2024 NLCD
Hydrologic Method:
Duda et al., "Estimation of magnitude and frequency of floods for rural, unregulated streams in and near Virginia and West Virginia." September 8, 2025.
Additional Model Notes:
None
END DESCRIPTION:
DSS Export Rating Curves= 0
DSS Export Rating Curve Sorted= 0
DSS Export Volume Flow Curves= 0
DXF OffsetX= 0
DXF OffsetY= 0
DXF ScaleX= 0
DXF ScaleY= 0

--- McLainRn.p01 (plan) ---

Plan Title=Floodplain
Program Version=4.00
Geom File=g01
Flow File=f01
K Sum by GR=0
Std Step Tol=0.01
Critical Tol=0.01
Num of Std Step Trials=20
Max Error Tol=0.3
Flow Tol Ratio=0.001
Split Flow NTrial=30
Split Flow Tol=0.02
Split Flow Ratio=0.02
Log Output Level=0
Friction Slope Method=1
Unsteady Friction Slope Method=2
Unsteady Bridges Friction Slope Method=1
Global Log Level=0
CheckData=False
Run HTab=0
Run UNet=0
Run PostProcess=0
UNET Theta=0
UNET Theta Warmup=0
UNET ZTol=0
UNET ZSATol=0
UNET MxIter=0
UNET MaxInSteps=0
UNET DtIC=0
UNET DtMin=0
UNET MaxCRTS=0
UNET WFStab=0
UNET SFStab=0
UNET WFX=0
UNET SFX=0
UNET DSS MLevel=0
UNET DZMax Abort=0
UNET Convert EG Bridges=0
UNET Use Existing IB Tables=0
UNET Froude Limit=0
UNET Froude Power=0
Write IC File=0
Echo Input=False
Echo Output=False
Write Detailed=0

--- McLainRn.f01 (steady flow) ---

Flow Title=Flow
Program Version=6.60
Number of Profiles= 1
Profile Names=P100yr
River Rch & RM=McLainRn,Main,3075
     719
Boundary for River Rch & Prof#=McLainRn,Main            , 1
Up Type= 0
Dn Type= 3
Dn Slope=0.038594
DSS Import GetInterval= 0
DSS Import GetPeak= 0
DSS Import FillOption= 0

--- McLainRn.g01 (geometry) ---

Geom Title=Geometry
Program Version=6.60

River Reach=McLainRn        ,Main
Reach XY= 30
  1629457.745199520691.8675887851629385.09891043520665.161295141
1629335.88791417 520592.43353961      1629230.58      520506.639
     1629174.647      520396.869     1629157.723       520333.36
     1629076.896      520218.593     1629030.302      520115.583
     1628976.908      520037.759     1628951.974      519961.194
     1628910.922      519920.393     1628861.809      519797.234
     1628794.072      519686.719      1628746.11      519647.981
     1628681.875      519614.167        1628595.      519600.625
     1628471.875      519485.417     1628411.733      519374.459
     1628338.015      519303.111     1628242.729      519234.446
     1628130.946      519026.479     1628025.657      519011.117
     1627975.946      519021.301     1627916.625      519019.442
     1627808.158      518970.815     1627758.624      518919.298
     1627726.408      518855.191     1627617.051      518612.957
     1627607.795      518544.692     1627584.365      518511.428

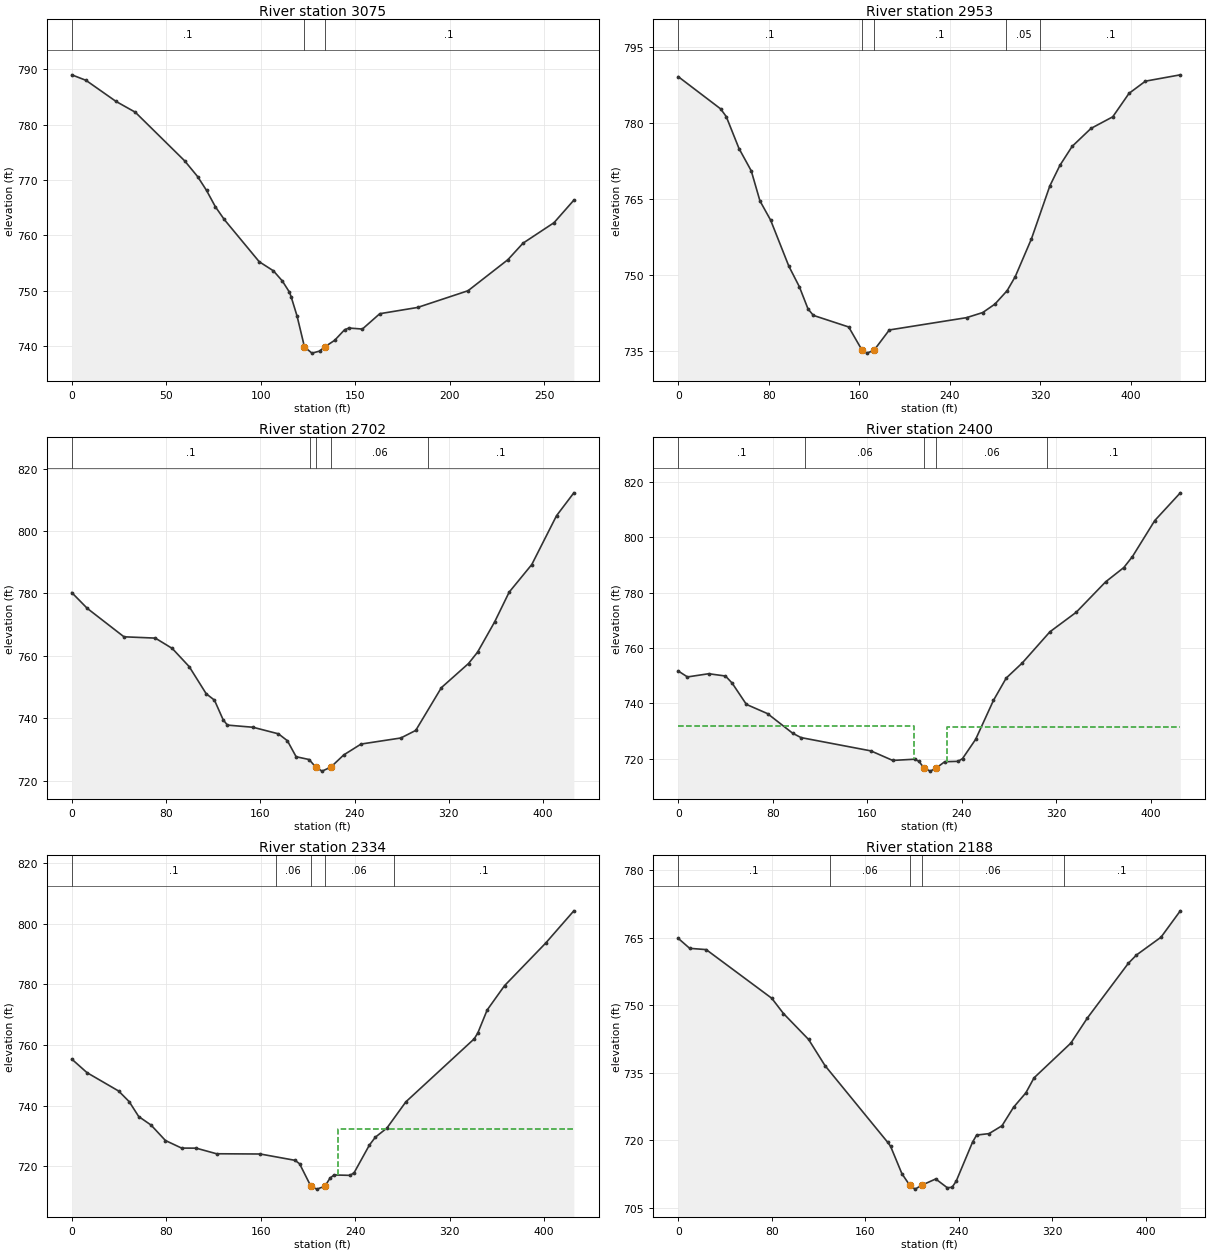
Type RM Length L Ch R = 1 ,3075    ,118.8,121.8,124.5
XS GIS Cut Line= 2
1629521.64064737520577.9154907011629370.51297633520796.488568651
#Sta/Elev= 30
       0     789     7.5  788.01    23.4   784.2    33.6  782.25    59.7  773.48
    66.6  770.62    71.3  768.13      76  765.17    80.7  762.87    99.2  755.24
   106.7   753.6   111.4  751.78   115.2  749.74   116.1   748.9   119.2  745.46
  123.16739.8368   127.1  738.73   131.1  739.09  133.78739.8321   139.1  741.04
   144.4  742.96   146.7  743.26   153.8  743.08     163  745.85     183  746.98
   209.7     750   230.8  755.61   238.8  758.59   255.2  762.29   265.7  766.36
#Mann= 3 ,-1,0
       0      .1       0  123.16    .045       0  133.78      .1       0
Bank Sta=123.16,133.78
XS Rating Curve= 0 ,0
Exp/Cntr(USF)=0,0
Exp/Cntr=0.3,0.1

Type RM Length L Ch R = 1 ,2953    ,250.5,250.7,250.5
XS GIS Cut Line= 2
1629503.95252813 520554.27729516 1629098.4178984520734.168297579
#Sta/Elev= 30
       0  789.18    37.4  782.82    42.4   781.3    53.7  774.97    64.5  770.57
    72.2  764.62    81.6  760.83    97.7  751.73     107  747.66   114.7  743.25
   119.4  741.99   150.6   739.7   162.5  735.08   166.7  734.53  172.92  735.08
   186.5  739.11   254.7  741.54     269  742.55   279.8  744.22   290.6  746.88
   297.8  749.67   312.1  757.14   328.3  767.57   337.2  771.64     348  775.39
   364.7  778.95   383.9  781.24   398.3  785.88   412.8  788.29   443.6  789.54
#Mann= 5 ,-1,0
       0      .1       0   162.5    .045       0  172.92      .1       0
     290     .05       0     320      .1       0
Bank Sta=162.5,172.92
XS Rating Curve= 0 ,0
Exp/Cntr(USF)=0,0
Exp/Cntr=0.3,0.1

Type RM Length L Ch R = 1 ,2702    ,302,302.2,301.7
XS GIS Cut Line= 6
1629391.41562584520343.8723395021629311.84098184520380.180009678
1629243.56159084520411.1156433371629154.09654668520456.435106501
1629089.47528484520495.3582570111629014.26185259520540.896879837
#Sta/Elev= 30
       0  780.27    13.2  775.19    44.3  766.09    70.9  765.67    85.3  762.35
    99.7  756.51   114.1  747.82   121.1  745.77   128.5  739.46   132.1  737.77
   153.8  737.08   175.4  734.97     183  732.76   190.4  727.63   201.4  726.73
  207.12724.2809   212.4  723.01   219.8  724.28   230.8   728.2   245.5  731.69
   279.3  733.64   291.9  736.06   313.7  749.79   336.7  757.52   344.4  761.17
   358.9  770.88   371.2  780.41   390.4  789.26   411.4  804.92   426.1  812.26
#Mann= 5 ,-1,0
       0      .1       0  202.43     .06       0  207.12    .045       0
   219.8     .06       0  302.72      .1       0
Bank Sta=207.12,219.8
XS Rating Curve= 0 ,0
Exp/Cntr(USF)=0,0
Exp/Cntr=0.3,0.1

Type RM Length L Ch R = 1 ,2400    ,66.2,66.2,66.1
XS GIS Cut Line= 6
1629245.21873976520073.4742582591629167.58831759520113.843928173
1629101.04744017520148.4465492521629012.32583284520194.582611844
1628945.78659584520229.1878575831628867.46293359520268.500443012
#Sta/Elev= 30
       0  751.68     7.8  749.53    25.8  750.69      40  749.86    45.6  747.33
    57.7  739.62    75.6  736.29    96.9  729.21     104  727.63   163.1  722.84
   181.6  719.39   200.1  719.83   203.7   719.1  208.11716.6701   213.4  715.53
   218.5  716.66   225.6  718.92     237  719.07   240.7  720.06   251.8     727
   266.9  741.07   277.7  749.13   291.3  754.58   314.7  765.83   336.9  772.85
   361.9  783.87   377.3  789.03   384.6     793   403.5     806   425.1  815.99
#Mann= 5 ,-1,0
       0      .1       0   107.5     .06       0  208.11    .045       0
   218.5     .06       0   312.5      .1       0
#XS Ineff= 2 , 0
          199.27  731.83  227.81          731.52
Permanent Ineff=
       F       F
Bank Sta=208.11,218.5
XS Rating Curve= 0 ,0
Exp/Cntr(USF)=0,0
Exp/Cntr=0.3,0.1

Type RM Length L Ch R = 1 ,2334    ,145.2,146,146.4
XS GIS Cut Line= 6
1629212.56910873520015.9914193471629134.93868656520056.361089261
1629068.39780914520090.9637103411628979.67620181520137.099772932
1628913.13696481520171.7050186711628834.81330256  520211.0176041
#Sta/Elev= 30
       0   755.4    12.9  750.93    39.7  744.87    48.6  741.38    56.7  736.45
    67.1  733.66    79.3  728.56      93  726.06   105.3  726.04   122.6  724.19
   159.6  724.11   189.1  722.02   192.9  720.88  202.47713.4599   207.6  712.53
   214.4  713.52   218.7  716.19   222.1   717.2   235.7  717.07   239.1  717.97
     252  727.06   257.1  729.67   266.8  732.65   282.9  741.32   340.7  762.06
   343.8  764.02   351.7  771.58   366.4   779.6   401.1  793.58   425.1  804.28
#Mann= 5 ,-1,0
       0      .1       0   172.5     .06       0  202.47    .045       0
   214.4     .06       0   272.5      .1       0
#XS Ineff= 2 , 0
                          225.83          732.28
Permanent Ineff=
       F       F
Bank Sta=202.47,214.4
XS Rating Curve= 0 ,0
Exp/Cntr(USF)=0,0
Exp/Cntr=0.3,0.1

Type RM Length L Ch R = 1 ,2188    ,82.6,82.2,82.4
XS GIS Cut Line= 2
1629152.40582415519913.0417269461628750.45986326520064.232409483
#Sta/Elev= 30
       0  764.91     9.8  762.69    23.9  762.41      80  751.59      90   748.2
   111.5  742.43   125.5  736.63   179.2  719.55   181.6  718.68   191.3  712.59
  197.94 710.043   202.6  709.16  208.32710.0328   220.2  711.42   230.1  709.47
   234.2  709.57   237.7  710.92   251.7   719.6   255.2  721.18   265.8   721.5
   276.9  723.25   286.8  727.37   297.3  730.56   304.3   733.9   335.8  741.63
   349.9   747.2   384.9  759.35   391.9  761.21   412.9  765.17   429.4  771.03
#Mann= 5 ,-1,0
       0      .1       0     130     .06       0  197.94    .045       0
  208.32     .06       0     330      .1       0
Bank Sta=197.94,208.32
XS Rating Curve= 0 ,0
Exp/Cntr(USF)=0,0
Exp/Cntr=0.3,0.1

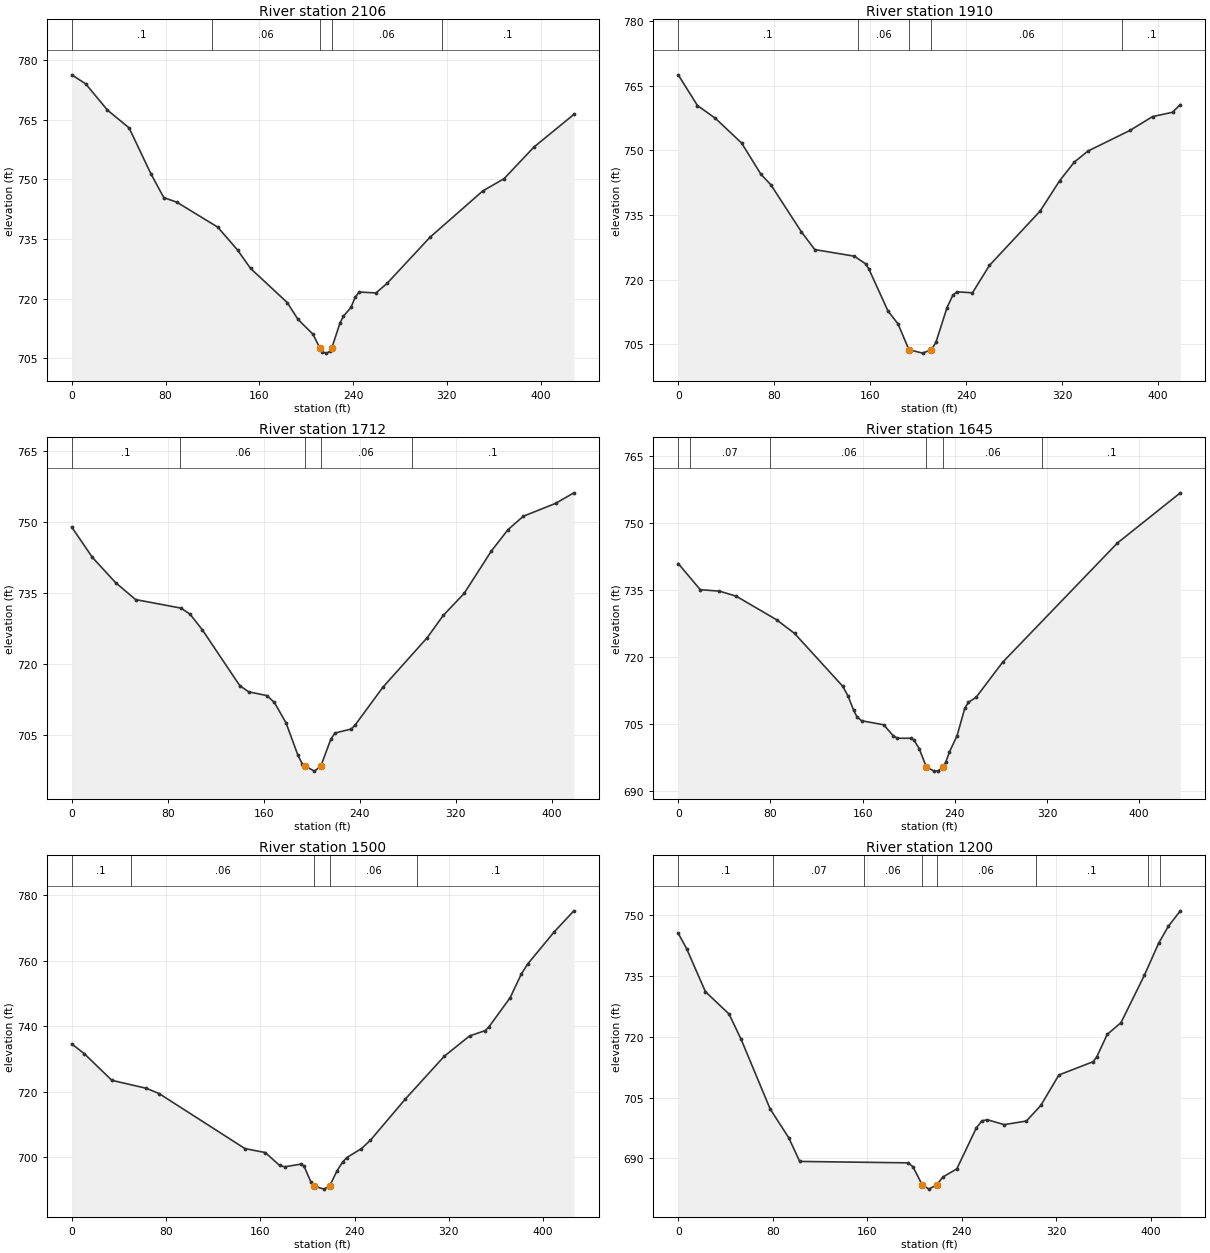
Type RM Length L Ch R = 1 ,2106    ,198.2,195.9,193.3
XS GIS Cut Line= 5
1629104.52193362519826.2127639521628941.61986237519911.284226788
1628864.64896284519939.6507070061628797.56707601519973.192634672
1628719.30509342 520012.32477425
#Sta/Elev= 30
       0  776.36    11.9  774.08    30.4  767.49    48.9  762.99    67.4   751.5
    78.5  745.42    89.6  744.28   124.5     738   141.4  732.23   152.5   727.6
   183.8  718.99     193  714.74   205.8     711  211.63707.5441   213.7  706.51
   217.2  706.25   220.7  706.72   221.8 707.541   228.8  713.83   231.8  715.56
   238.2  717.77   241.7  720.29   245.2  721.64   259.5  721.42   268.9   723.8
   305.6  735.45   350.5  747.08   368.9  750.23   394.2  758.15   428.3  766.38
#Mann= 5 ,-1,0
       0      .1       0     120     .06       0  211.63    .045       0
   221.8     .06       0  315.81      .1       0
Bank Sta=211.63,221.8
XS Rating Curve= 0 ,0
Exp/Cntr(USF)=0,0
Exp/Cntr=0.3,0.1

Type RM Length L Ch R = 1 ,1910    ,202.4,197.8,192.6
XS GIS Cut Line= 2
1628995.29816987519624.0903489661628658.75555535519872.761674795
#Sta/Elev= 30
       0  767.52      16   760.4    30.9  757.45    52.8   751.7      69  744.42
    77.2  742.01   102.7  731.07   113.8  726.98   146.7  725.45   156.1  723.69
   158.8  722.51   174.8  712.73   183.2  709.73  192.22703.7686   203.6  702.96
  210.93703.7374   214.7  705.44     224  713.53   228.8  716.39   232.2  717.18
   245.2  716.96   259.3   723.3   301.5  735.89   317.9  742.98   330.1  747.29
   341.4  749.83   376.6  754.65   395.3  757.84   411.9  758.83   418.4  760.63
#Mann= 5 ,-1,0
       0      .1       0     150     .06       0  192.22    .045       0
  210.93     .06       0     370      .1       0
Bank Sta=192.22,210.93
XS Rating Curve= 0 ,0
Exp/Cntr(USF)=0,0
Exp/Cntr=0.3,0.1

Type RM Length L Ch R = 1 ,1712    ,67.9,66.7,65.2
XS GIS Cut Line= 4
1628782.43767669519441.981967346 1628691.6347653519602.081837419
1628678.49223866519649.2754558361628645.03853446519831.478666181
#Sta/Elev= 30
       0   748.9    17.2   742.5    36.5  737.16    53.2  733.58    90.9  731.78
    98.5  730.51   108.7  727.22     140  715.37   147.5  714.07   162.6  713.28
   168.8  711.83   178.5  707.52   188.5  700.62   191.9  698.91   194.5  698.36
   202.2  697.31   207.4  698.33   215.8  704.02   219.2  705.36   232.8  706.21
   236.1  707.06   259.2  715.05   296.2  725.55   309.5  730.23   326.9  734.88
   349.6  743.86   363.5  748.38   376.2   751.2   403.1  753.92   418.3  756.15
#Mann= 5 ,-1,0
       0      .1       0      90     .06       0   194.5    .045       0
   207.4     .06       0  283.05      .1       0
Bank Sta=194.5,207.4
XS Rating Curve= 0 ,0
Exp/Cntr(USF)=0,0
Exp/Cntr=0.3,0.1

Type RM Length L Ch R = 1 ,1645    ,138.4,145.1,146.8
XS GIS Cut Line= 3
1628733.45189555519416.2943016251628622.93519419519590.134085921
1628610.98744269519819.530914683
#Sta/Elev= 30
       0  740.94    19.1  735.09    35.8  734.76    50.3  733.64    85.3  728.37
   100.9  725.32   142.7  713.52   147.5  711.26   152.2  708.13   155.3   706.6
   159.2  705.79   178.4  704.88   186.4  702.48   190.2  701.88   201.9  701.88
   204.5  701.51   209.1  699.56   215.4   695.4   222.3  694.53   225.6   694.6
  229.59695.3743   232.1   696.5   235.4  698.84     242  702.47   248.6  708.54
   251.8  709.92   258.4     711   281.4  718.84   381.1  745.52   435.7  756.74
#Mann= 6 ,-1,0
       0      .1       0      10     .07       0      80     .06       0
   215.4    .045       0  229.59     .06       0     316      .1       0
Bank Sta=215.4,229.59
XS Rating Curve= 0 ,0
Exp/Cntr(USF)=0,0
Exp/Cntr=0.3,0.1

Type RM Length L Ch R = 1 ,1500    ,299.3,300,299.2
XS GIS Cut Line= 6
1628652.14971593519362.5462181721628588.30568351519423.525755003
1628540.16109475519481.1388287541628480.61823484519561.480531588
 1628433.8374885519620.1752960831628375.82448117519685.971424341
#Sta/Elev= 30
       0  734.58    10.6  731.61      34  723.46    63.3  721.02    74.1  719.41
     147  702.58   164.2  701.38   176.3  697.47   180.7  697.01   194.7  697.86
   197.1  697.24     203  692.31  205.67691.1323     214  690.19  218.79691.1341
   225.2  695.83   229.9   698.5   233.5  699.86   245.8  702.57   253.4  705.12
     283   717.7   316.2  730.84   337.6  737.02   350.7  738.65   353.7  739.63
   372.1  748.76   381.6  756.03     387  759.06   409.5  768.87   426.1  775.28
#Mann= 5 ,-1,0
       0      .1       0      50     .06       0  205.67    .045       0
  218.79     .06       0  293.37      .1       0
Bank Sta=205.67,218.79
XS Rating Curve= 0 ,0
Exp/Cntr(USF)=0,0
Exp/Cntr=0.3,0.1

Type RM Length L Ch R = 1 ,1200    ,287,290.8,293.7
XS GIS Cut Line= 6
1628445.12749217 519118.301299841628395.33986209519190.255880341
1628352.66507867519251.9312819241628295.76558617519334.165369421
1628253.09113084519395.8410990831628202.37797767519467.155260921
#Sta/Elev= 30
       0  745.43     7.1  741.65      23  731.06      43  725.56    53.2  719.35
    77.8  702.19    93.6  695.07   102.8  689.27   194.6  688.92   198.6  687.99
   206.5  683.52   212.2  682.45  218.79683.5223     224  685.43   235.8  687.44
   252.3  697.49     257  699.26   261.7  699.53   275.9  698.33   294.7  699.21
   306.9  703.05   322.2  710.55   351.3  713.83   354.3  715.02   363.1  720.53
   374.8  723.44   394.6  735.11   406.6  742.95   414.8  747.13     425  750.96
#Mann= 8 ,-1,0
       0      .1       0      80     .07       0   157.5     .06       0
   206.5    .045       0  218.79     .06       0   302.5      .1       0
   397.5     .06       0   407.5      .1       0
Bank Sta=206.5,218.79
XS Rating Curve= 0 ,0
Exp/Cntr(USF)=0,0
Exp/Cntr=0.3,0.1

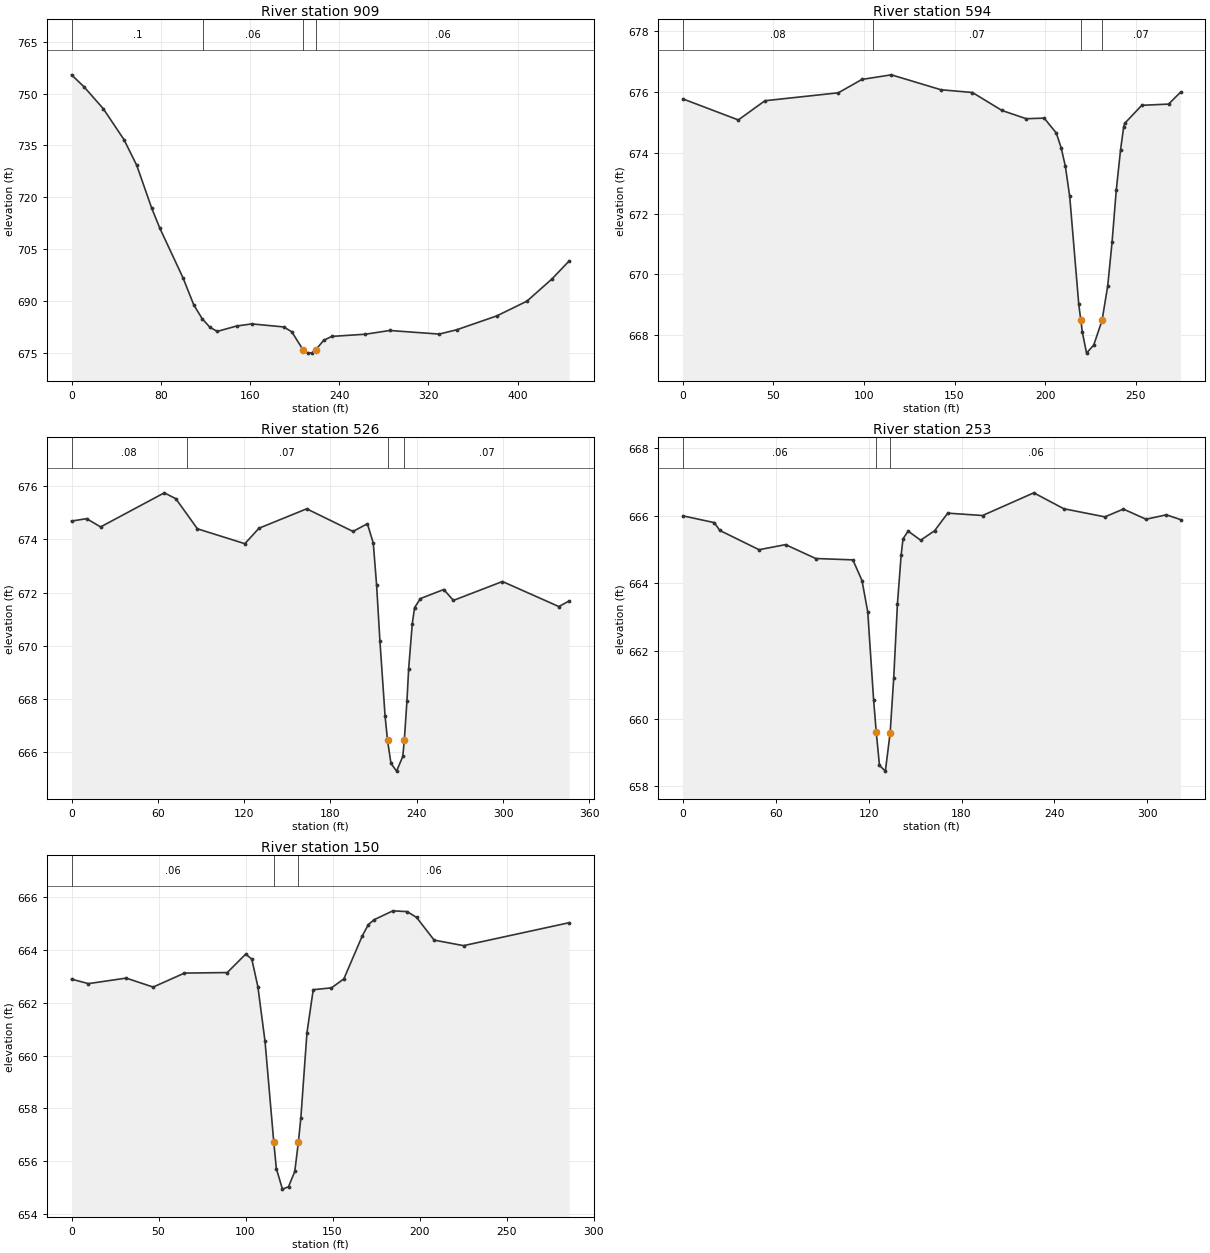
Type RM Length L Ch R = 1 ,909     ,318.5,315.3,312.5
XS GIS Cut Line= 6
1628353.07485476518992.1453841781628272.21609259519026.611850679
1628200.39307351519048.3995367591628108.29286401519088.749193594
1628056.35136685519153.9951260831628003.78290242519238.282687172
#Sta/Elev= 30
       0   755.4    11.3   751.9    28.5   745.6      47   736.7    58.5  729.23
    71.9  716.87    79.1  711.15     100  696.74   109.6  688.96   117.1  684.99
     124  682.52   130.6   681.3     148  682.86   161.7  683.47   190.3  682.59
   197.5  681.18  207.39676.0735   211.8  675.03   215.4  675.08  219.15676.0732
   226.1  678.73   233.3  679.86   263.5  680.49   285.3  681.57   329.7  680.53
   345.5  681.79   381.3  685.78   408.3  690.03   430.8  696.46   446.2  701.66
#Mann= 4 ,-1,0
       0      .1       0   117.9     .06       0  207.39    .045       0
  219.15     .06       0
Bank Sta=207.39,219.15
XS Rating Curve= 0 ,0
Exp/Cntr(USF)=0,0
Exp/Cntr=0.3,0.1

Type RM Length L Ch R = 1 ,594     ,67.3,67.4,67.2
XS GIS Cut Line= 4
1628043.92361625518858.2192850231627980.25881279518897.340538421
1627893.93094275518973.0951822411627842.15735292519040.799107397
#Sta/Elev= 30
       0  675.76    30.6  675.07    45.3   675.7    85.8  675.96    98.9   676.4
   115.1  676.55   142.5  676.06   159.9  675.97   176.2  675.38   189.6  675.11
   199.5  675.13   206.2  674.64   208.9  674.15   211.2  673.55   213.6  672.56
   218.6  669.02  219.73668.5002   220.6   668.1   222.9  667.42   226.9  667.69
  231.46668.4932   234.6  669.63     237  671.07   239.3  672.76   241.7   674.1
   243.4  674.84     244  674.96   253.4  675.55   268.2  675.59   274.8  675.98
#Mann= 4 ,-1,0
       0     .08       0  104.72     .07       0  219.73    .045       0
  231.46     .07       0
Bank Sta=219.73,231.46
XS Rating Curve= 0 ,0
Exp/Cntr(USF)=0,0
Exp/Cntr=0.3,0.1

Type RM Length L Ch R = 1 ,526     ,270.4,273.6,275.1
XS GIS Cut Line= 5
1627985.09623355 518830.616627751627895.41882215518894.439966511
1627831.34568558 518946.148111811627787.50617109519004.600797799
1627740.29438625519069.798024479
#Sta/Elev= 30
       0  674.69    10.5  674.78    20.2  674.47    64.5  675.75    72.5  675.53
    87.5   674.4   120.5  673.84   130.3  674.42   163.5  675.15   195.7   674.3
   205.7  674.59   209.8  673.86   212.1  672.29   214.4   670.2     218  667.37
  219.71666.4512   222.1  665.59     226   665.3   230.3  665.85   231.4666.4814
   233.2  667.93   234.4  669.15   236.9  670.83   238.5  671.44   242.6  671.78
   258.8  672.12   265.5  671.71   299.6  672.42   338.8  671.48     346  671.69
#Mann= 4 ,-1,0
       0     .08       0      80     .07       0  219.71    .045       0
   231.4     .07       0
Bank Sta=219.71,231.4
XS Rating Curve= 0 ,0
Exp/Cntr(USF)=0,0
Exp/Cntr=0.3,0.1

Type RM Length L Ch R = 1 ,253     ,102.2,103.1,103.6
XS GIS Cut Line= 5
1627790.91719479 518686.417084141627735.72513371518706.484871628
1627649.19873196518756.8053090441627585.24118272518796.190072807
1627509.37420847518840.013147878
#Sta/Elev= 30
       0  665.99    20.3  665.79    23.8  665.56    49.2  664.99    66.3  665.14
    85.8  664.73   109.8  664.69   115.7  664.08   119.4  663.16   123.2  660.56
124.9266659.5924     127  658.62   130.8  658.45133.8866659.5798   136.2   661.2
   138.6  663.39     141  664.83   142.2  665.31   145.5  665.54   153.6  665.27
   162.6  665.55   171.1  666.07   193.6     666   226.7  666.67   246.1   666.2
   272.6  665.96   284.6  666.19   299.2  665.89   312.3  666.02   321.5  665.88
#Mann= 3 ,-1,0
       0     .06       0124.9266    .045       0133.8866     .06       0
Bank Sta=124.9266,133.8866
XS Rating Curve= 0 ,0
Exp/Cntr(USF)=0,0
Exp/Cntr=0.3,0.1

Type RM Length L Ch R = 1 ,150     ,,,
XS GIS Cut Line= 4
1627746.15542824518660.5610686081627676.76714952518631.417991547
1627564.35813801518675.8264899251627543.54165439518763.255721106
#Sta/Elev= 30
       0   662.9     9.7  662.73    31.4  662.94    46.9   662.6    64.9  663.13
    89.5  663.15   100.1  663.85   103.6  663.66   107.1  662.61   111.2  660.54
   116.2  656.74   117.7  655.72   121.2  654.94   124.7  655.03   128.3  655.61
   130.4  656.74   131.8  657.65   135.3  660.87   138.9   662.5   149.4  662.57
   156.5  662.91   167.1  664.54   170.6  664.97   174.1  665.16   184.7  665.49
   192.9  665.46   198.3  665.24   208.4  664.38   225.3  664.17     286  665.04
#Mann= 3 ,-1,0
       0     .06       0   116.2    .045       0   130.4     .06       0
Bank Sta=116.2,130.4
XS Rating Curve= 0 ,0
Exp/Cntr(USF)=0,0
Exp/Cntr=0.3,0.1
LCMann Table=0

Chan Stop Cuts=-1
Use User Specified Reach Order=0
Composite Channel Slope=5